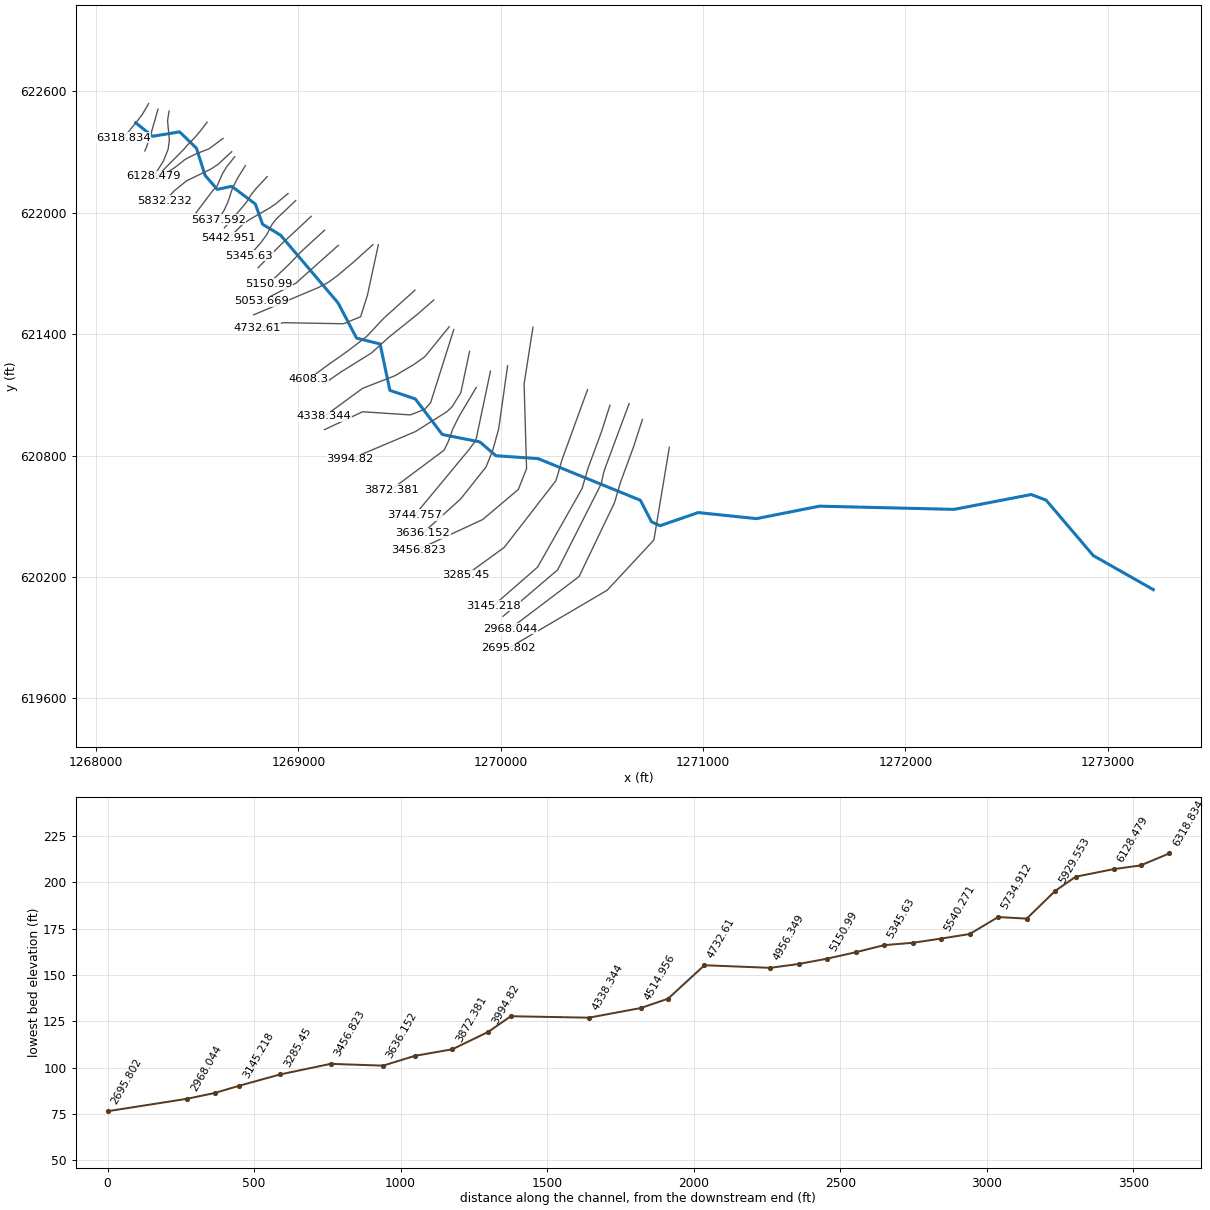
--- 551_ras.prj (project) ---

Proj Title=551
Current Plan=p01
Default Exp/Contr=0.3,0.1
English Units
Geom File=g01
Flow File=f01
Plan File=p01
Y Axis Title=Elevation
X Axis Title(PF)=Main Channel Distance
X Axis Title(XS)=Station
BEGIN DESCRIPTION:
RFD model 551 exported to HEC-RAS
END DESCRIPTION:

--- 551_ras.p01 (plan) ---

Plan Title=Plan 01
Program Version=4.10
Short Identifier=Plan 01
Geom File=g01
Flow File=f01
Subcritical Flow
Calc Critical at every XS
Secant Critical Depth

--- 551_ras.f01 (steady flow) ---

Flow Title=Flow 01
Program Version=5.01
Number of Profiles= 5
Profile Names=10yr,25yr,50yr,100yr,500yr
River Rch & RM=551,30,6318.834
  384.38  458.63  546.79  583.34  684.22
River Rch & RM=551,30,6221.514
  386.14  461.03  549.74  586.88  688.97
River Rch & RM=551,30,6128.479
  429.63  521.02  623.47  676.18  810.04
River Rch & RM=551,30,5999.224
  434.06  527.18  631.05  685.45  822.74
River Rch & RM=551,30,5929.553
  437.69  532.24   637.3  693.08  833.22
River Rch & RM=551,30,5734.912
   500.7  620.95  746.83  828.53 1021.79
River Rch & RM=551,30,5637.592
  504.79  626.77  754.04  837.53 1034.49
River Rch & RM=551,30,5540.271
  508.26   631.7  760.15  845.17 1045.29
River Rch & RM=551,30, 5345.63
  540.59  677.97  817.49  917.26 1147.79
River Rch & RM=551,30, 5248.31
  545.27  684.69  825.84   927.8 1162.89
River Rch & RM=551,30, 5150.99
  548.86  689.87  832.26  935.93 1174.54
River Rch & RM=551,30,5053.669
   550.9  692.81  835.91  940.55 1181.16
River Rch & RM=551,30,4956.349
  556.95  701.53  846.74  954.28 1200.89
River Rch & RM=551,30, 4732.61
  593.11  753.98  911.95 1037.37 1321.12
River Rch & RM=551,30,  4608.3
  594.47  755.96  914.41 1040.53 1325.72
River Rch & RM=551,30,4338.344
  608.24  776.07  939.45 1072.64 1372.59
River Rch & RM=551,30, 4071.91
  627.42  804.18  974.48 1117.77 1438.78
River Rch & RM=551,30,3872.381
  628.25   805.4  976.01 1119.74 1441.68
River Rch & RM=551,30,3744.757
  632.39  811.48  983.58 1129.53 1456.09
River Rch & RM=551,30,3636.152
  635.25   815.7  988.85 1136.33 1466.13
River Rch & RM=551,30,3456.823
  638.51  820.49  994.83 1144.07 1477.54
River Rch & RM=551,30, 3285.45
   658.3  849.71 1031.29 1191.37 1547.57
River Rch & RM=551,30,3145.218
  662.92  856.54 1039.83 1202.47 1564.06
River Rch & RM=551,30,3061.561
  664.44   858.8 1042.65 1206.15 1569.53
River Rch & RM=551,30,2968.044
  665.21  859.93 1044.06 1207.99 1572.26
River Rch & RM=551,30,2695.802
  670.88  868.34 1054.57 1221.68 1592.64
Boundary for River Rch & Prof#=551,30,1
Up Type= 0
Dn Type= 2
Boundary for River Rch & Prof#=551,30,2
Up Type= 0
Dn Type= 2
Boundary for River Rch & Prof#=551,30,2
Up Type= 0
Dn Type= 2
Boundary for River Rch & Prof#=551,30,2
Up Type= 0
Dn Type= 2
Boundary for River Rch & Prof#=551,30,2
Up Type= 0
Dn Type= 2

--- 551_ras.g01 (geometry) ---

Geom Title=551
Program Version=4.10

River Reach=551,30
Reach XY= 30
1268195.25181401622445.353445917 1268279.4184539622378.686796591
1268412.75174856622400.3534529361268496.08505493622319.520141169
1268538.58503848622185.3535130621268598.58501869622116.186865181
 1268670.2516647622131.1868586241268786.91829437622043.686881199
1268822.75161415 621943.686909841268911.91825294621889.520256624
1269196.08482587621554.5203477741269287.24605858621381.012876853
1269403.58475876621352.0204018211269451.91807112621122.853801802
1269577.75136605621080.3538107131269711.08465496620904.520525694
 1269896.9179323620867.8538644761269976.08457369620799.520549119
1270184.41784507620785.3538805541270690.25102305620579.520593509
1270745.25100368620472.8539569231270786.91765755620453.687294751
 1270976.0842703620518.6872698811271263.58418453620488.687270373
1271575.25076109620550.3539096271272241.08389738620534.520561472
1272621.91712052620607.8538618531272695.25043142620580.353867888
1272928.58368781620306.1872758271273225.25026202 620137.85398373

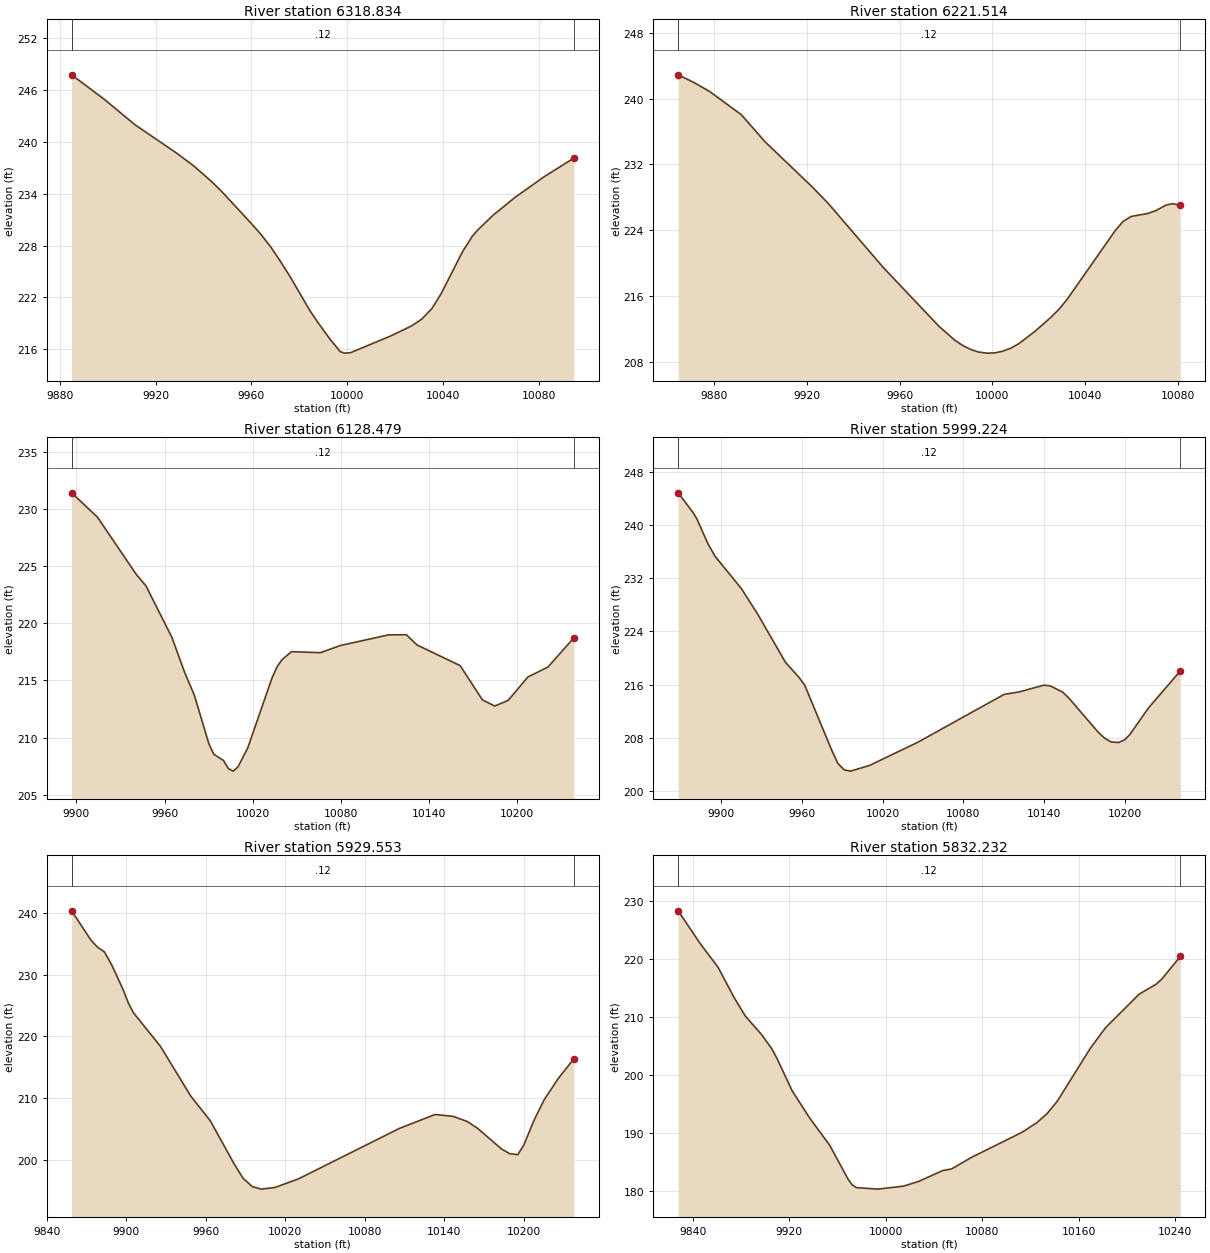
Type RM Length L Ch R = 1 ,6318.834,97.320300,97.320300,97.320300
XS GIS Cut Line= 6
1268259.32765555622540.5351860371268255.31056768 622532.44704695
1268229.23954788 622488.437049911268204.84198916622455.467251182
1268196.66061783622445.4770251661268135.69598418 622371.66008541
#Sta/Elev= 30
9884.889247.76829898.503244.93939911.377241.98569928.531238.75279936.157237.1699
9943.563235.37159947.775234.21499960.019230.55239964.101229.26819968.182227.8172
9972.263226.12819976.345 224.3289984.508220.45659987.792 219.113 9992.97217.1317
9997.168215.7203    9999215.554310001.43215.601810018.45217.568510026.96218.7078
10031.21219.494410035.47220.718410039.36222.467310048.23227.283910052.48229.1483
10054.82229.863310060.99231.512110070.28233.601510082.27235.953910094.74238.1258
#Mann= 3 , 0 , 0
9884.889    0.12       09884.889    0.12       010094.74    0.12       0
#XS Ineff= 2 , 0
       0                               0
Bank Sta=9884.889,10094.74
Exp/Cntr=0.3,0.1

Type RM Length L Ch R = 1 ,6221.514,93.034700,93.034700,93.034700
XS GIS Cut Line= 6
1268306.45165324622512.2607874571268304.11020342622506.093099684
1268270.22287023 622387.934814111268268.72848916622383.185914442
 1268247.5604085622321.6591783761268240.69336998622306.050450787
#Sta/Elev= 30
9864.503 242.8759871.249241.95299878.076240.85639891.728238.04249901.967234.7537
9922.446229.24469929.272227.26229953.164219.44129977.055212.35129983.881 210.661
9987.295210.02879990.708209.55019994.022209.24239997.561209.105710001.01209.1292
10004.48209.334310007.95209.703810011.42210.242610018.36211.7385 10025.3213.4536
10028.77214.431110032.24 215.60910053.06223.980810056.53225.1104   10060225.6979
10067.04226.040810070.62226.404610075.06227.084310077.79227.227110081.12 227.083
#Mann= 3 , 0 , 0
9864.503    0.12       09864.503    0.12       010081.12    0.12       0
#XS Ineff= 2 , 0
       0                               0
Bank Sta=9864.503,10081.12
Exp/Cntr=0.3,0.1

Type RM Length L Ch R = 1 ,6128.479,129.255600,129.255600,129.255600
XS GIS Cut Line= 6
1268360.78138591622503.357381344 1268352.9952058622456.166572481
1268362.18333255622360.5832842291268356.05620824622314.783491775
1268332.41997255622255.7855849861268285.82741283622181.425392434
#Sta/Elev= 30
9896.737231.41999914.265229.29969940.771224.27419947.355223.26989964.975218.7693
9973.665215.69629980.275213.69969990.189209.43989993.494208.536510000.11207.9902
10003.42207.280410006.72207.057310010.03207.436810016.64 209.09610033.16215.2232
10036.47216.163110039.77216.790210046.36217.5163 10066.1217.4258 10079.5218.0476
10112.47218.987710124.57218.9975 10131.8218.1056 10161.2216.294610176.38 213.294
10184.77212.756810193.92213.250810207.28 215.29710220.98216.167810238.55218.7165
#Mann= 3 , 0 , 0
9896.737    0.12       09896.737    0.12       010238.55    0.12       0
#XS Ineff= 2 , 0
       0                10066.63       0
Bank Sta=9896.737,10238.55
Exp/Cntr=0.3,0.1

Type RM Length L Ch R = 1 ,5999.224,69.670900,69.670900,69.670900
XS GIS Cut Line= 6
1268548.47165647622448.110305369 1268516.3027052622406.175044969
1268488.91116738622373.7120265071268448.09099248622331.692671359
1268432.77623734622313.5097359871268295.52513841 622174.84968242
#Sta/Elev= 30
9868.224 244.874 9879.37241.88039882.162240.92929890.151237.28849895.541235.3364
9915.242230.43129927.501226.52629947.851219.35959958.026217.06629962.239215.8846
9982.051206.20239986.778204.13449991.505203.16039996.231202.967310010.29203.8209
10045.91207.291610110.28214.528310121.36 214.89410139.82215.917410144.44 215.805
10153.67214.865410158.29213.962210180.24208.7849 10184.9207.921210189.57207.3602
10195.22207.275410199.84207.704910203.56 208.48810217.55212.525310241.01218.0495
#Mann= 3 , 0 , 0
9868.224    0.12       09868.224    0.12       010241.01    0.12       0
#XS Ineff= 2 , 0
       0                10110.73       0
Bank Sta=9868.224,10241.01
Exp/Cntr=0.3,0.1

Type RM Length L Ch R = 1 ,5929.553,97.320400,97.320400,97.320400
XS GIS Cut Line= 6
 1268627.3156451622367.9679676151268557.60925731622316.456119046
1268490.26631671622290.1519598071268441.61872244 622265.55216144
1268388.74759644 622223.932410211268306.37583286622171.594474092
#Sta/Elev= 30
9858.854240.27699873.534235.51079878.521234.37699883.509233.67069888.891231.6329
9897.629227.58699901.712225.36619905.427223.84629925.906218.3942 9948.84 210.342
9963.528206.37389981.242199.5184 9988.22197.09849995.198195.764410002.09195.3599
10012.41195.637210030.12197.029310106.07205.1515 10133.1207.4068 10146.5207.1077
10157.17206.295910164.94205.2082 10183.2201.843310189.32201.083610195.44200.9265
10199.93202.430410207.67206.451310215.47209.812210226.03213.226610237.72216.3804
#Mann= 3 , 0 , 0
9858.854    0.12       09858.854    0.12       010237.72    0.12       0
#XS Ineff= 2 , 0
       0                10117.53       0
Bank Sta=9858.854,10237.72
Exp/Cntr=0.3,0.1

Type RM Length L Ch R = 1 ,5832.232,97.320300,97.320300,97.320300
XS GIS Cut Line= 6
1268669.94134593622302.4141051621268602.49579898622239.413871661
1268567.12821826622216.612290651 1268446.7928139622158.168651968
1268389.66213274622112.025067538 1268337.3167021622058.913421512
#Sta/Elev= 30
9827.727228.3605 9845.72 222.793 9860.91218.60279874.094213.41869883.439210.2178
9896.832207.04639905.348204.58829909.605202.9617 9922.19197.36429936.814192.6327
9953.418187.94989968.849182.02939972.038181.12099975.615180.63459993.503180.3739
10014.85180.897510027.45181.7229 10047.1183.570410054.51183.855410071.41185.8875
10112.86190.158810125.09 191.80710133.59193.348310142.26195.541310169.73  204.68
10182.18208.191710210.22214.000610224.24215.703610228.92216.5868 10244.3220.4863
#Mann= 3 , 0 , 0
9827.727    0.12       09827.727    0.12       0 10244.3    0.12       0
#XS Ineff= 2 , 0
       0                10085.64       0
Bank Sta=9827.727,10244.3
Exp/Cntr=0.3,0.1

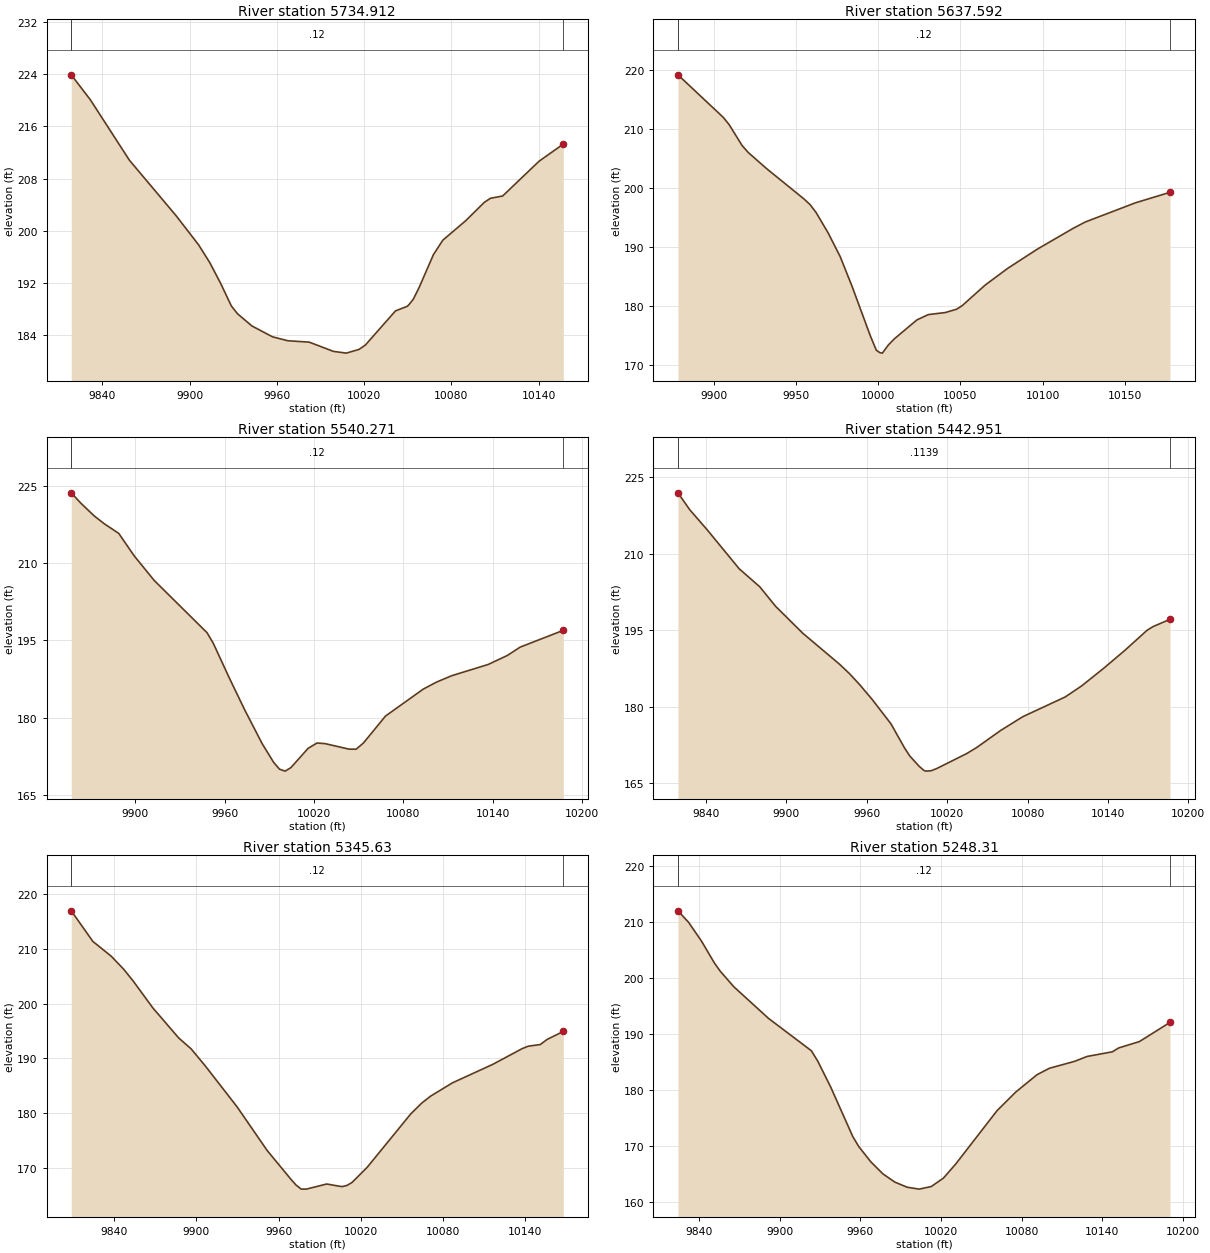
Type RM Length L Ch R = 1 ,5734.912,97.320400,97.320400,97.320400
XS GIS Cut Line= 6
1268684.90871835622277.4684844911268643.97684729622226.019315332
1268624.27964878622193.3780077841268598.02237251622133.220702484
1268573.52232137622105.9320614041268493.89820126622000.677365735
#Sta/Elev= 30
9818.715223.9036 9831.92220.05229858.659210.82389890.907202.27299906.235197.8466
9913.898 195.1349921.562191.86559928.716188.49359932.914 187.2919942.864185.4114
9957.012183.74319967.623183.13419982.282182.9239    9999 181.50410007.78181.2378
10016.56181.810410020.95182.4862 10041.6187.709910049.75188.421110051.07188.7191
10053.82189.490210057.89191.306710067.69196.334210074.18198.558610089.84201.5271
 10102.8204.375710106.96204.9799 10115.3205.327110140.31210.655410157.01213.2944
#Mann= 3 , 0 , 0
9818.715    0.12       09818.715    0.12       010157.01    0.12       0
#XS Ineff= 2 , 0
       0                               0
Bank Sta=9818.715,10157.01
Exp/Cntr=0.3,0.1

Type RM Length L Ch R = 1 ,5637.592,97.320400,97.320400,97.320400
XS GIS Cut Line= 6
1268737.65038088622233.1924431621268698.63505626622170.937222794
1268673.27528864622120.1697113361268652.13990253622055.620071799
1268632.53688049622012.9400743991268603.48768483621966.956037456
#Sta/Elev= 30
9878.014219.12819905.593 211.9419909.221 210.6979917.054207.17999920.839205.9883
9932.192203.22129954.794198.1272 9958.46197.17849962.127195.84419969.459192.3981
9976.792188.38979984.125183.28459995.125175.00769998.791172.5595   10001172.1417
10002.48172.067910006.14173.455210009.72174.473910023.53177.691410030.43178.5814
10040.79178.930310047.69179.496710051.14 180.11110064.95183.550310078.88186.4234
10096.93189.670410118.59193.159810125.97194.237810156.54197.485210177.59199.2618
#Mann= 3 , 0 , 0
9878.014    0.12       09878.014    0.12       010177.59    0.12       0
#XS Ineff= 2 , 0
       0                               0
Bank Sta=9878.014,10177.59
Exp/Cntr=0.3,0.1

Type RM Length L Ch R = 1 ,5540.271,97.320400,97.320400,97.320400
XS GIS Cut Line= 6
1268845.60728052622179.213993311 1268787.7951608622117.312201008
1268766.35834804622090.2769531611268744.10111997622054.630356148
1268732.36063206 622038.876966731268634.14259762621926.022918442
#Sta/Elev= 30
9856.955 223.6689863.288221.68729872.266219.20799879.233 217.6369888.846215.7889
9899.201 211.4329912.669206.64839948.116196.51239952.303194.46869962.849187.8705
 9973.41181.53419985.197174.93519992.892171.31529996.782169.996410000.63169.6143
10004.48170.298210016.02174.0369   10022175.073810027.49174.952610043.35173.8941
10048.28173.865810053.22175.086310068.02180.311410093.32185.5333 10102.1186.8808
10112.45188.144910136.98190.330110149.85192.079510158.43193.693910187.45196.9634
#Mann= 3 , 0 , 0
9856.955    0.12       09856.955    0.12       010187.45    0.12       0
#XS Ineff= 2 , 0
       0                               0
Bank Sta=9856.955,10187.45
Exp/Cntr=0.3,0.1

Type RM Length L Ch R = 1 ,5442.951,97.320300,97.320300,97.320300
XS GIS Cut Line= 6
1268948.75739503622095.5859122131268887.89939818622044.905675799
1268857.72659162622024.3022542151268753.70239177621964.243197501
1268720.18701556621939.6232804361268656.34681497621876.482168103
#Sta/Elev= 30
9818.948221.90579827.807218.57899840.616214.70899864.685207.01159880.065203.4766
 9891.85199.66029912.151194.37659939.618188.29929947.049186.4463 9954.48184.3403
9963.998181.3861 9977.98176.61979988.039171.93289992.001170.3217    9999 168.299
10002.51167.4896   10004167.3354   10008167.412210012.01167.818710034.66170.7926
 10042.2171.996810059.84175.297110076.47178.014110108.19181.8881 10120.4184.0516
10137.01187.536710152.66191.019610169.27194.9594 10173.7195.673110186.36197.1104
#Mann= 3 , 0 , 0
9818.948  0.1139       09818.948  0.1139       010186.36  0.1139       0
#XS Ineff= 2 , 0
       0                               0
Bank Sta=9818.948,10186.36
Exp/Cntr=0.3,0.1

Type RM Length L Ch R = 1 , 5345.63,97.320400,97.320400,97.320400
XS GIS Cut Line= 6
1268986.30004233622060.7463355061268891.36854997621970.761709243
1268870.15443709621944.025446877 1268843.6339995621892.945369795
1268815.27795687621853.6595565971268756.79609653621788.250001912
#Sta/Elev= 30
9808.915 216.9969824.649211.39869838.065208.6881 9847.01206.34089853.823204.2294
9868.306199.25699887.259193.72439896.218191.75849906.538188.64139929.832181.1131
9951.773 173.1229969.203167.82189972.714166.83189976.556166.07229980.268166.0698
9995.114167.006610006.15166.526510009.85166.739410013.54167.284110024.51170.0256
10056.33179.815610064.42181.819210070.85183.083610086.76185.512510116.46188.9352
10137.63191.781610142.01 192.22310150.77192.523810156.01193.489910167.62194.9268
#Mann= 3 , 0 , 0
9808.915    0.12       09808.915    0.12       010167.62    0.12       0
#XS Ineff= 2 , 0
       0                               0
Bank Sta=9808.915,10167.62
Exp/Cntr=0.3,0.1

Type RM Length L Ch R = 1 , 5248.31,97.320400,97.320400,97.320400
XS GIS Cut Line= 5
1269063.32007861621983.1065754891268935.60939175621863.963260189
1268934.10423833621862.6462509781268904.79899028621834.703122392
1268800.29387025621728.564401045
#Sta/Elev= 30
9824.343212.00679832.217209.96499841.836 206.6049851.455202.68819855.723201.2353
9865.883198.43469891.618192.79039923.598186.98189928.407185.10659938.026180.4691
9954.434171.63149958.921169.82649967.895167.10579976.869164.94779985.842 163.469
9994.816162.575210003.76162.228610012.83162.693210021.89164.204610030.96166.7061
10061.77176.265910075.58179.569410091.42182.684810100.77183.850510119.47185.0849
10128.83185.964710147.53 186.78810152.21187.478810167.67188.620410190.44192.0522
#Mann= 3 , 0 , 0
9824.343    0.12       09824.343    0.12       010190.44    0.12       0
#XS Ineff= 2 , 0
       0                               0
Bank Sta=9824.343,10190.44
Exp/Cntr=0.3,0.1

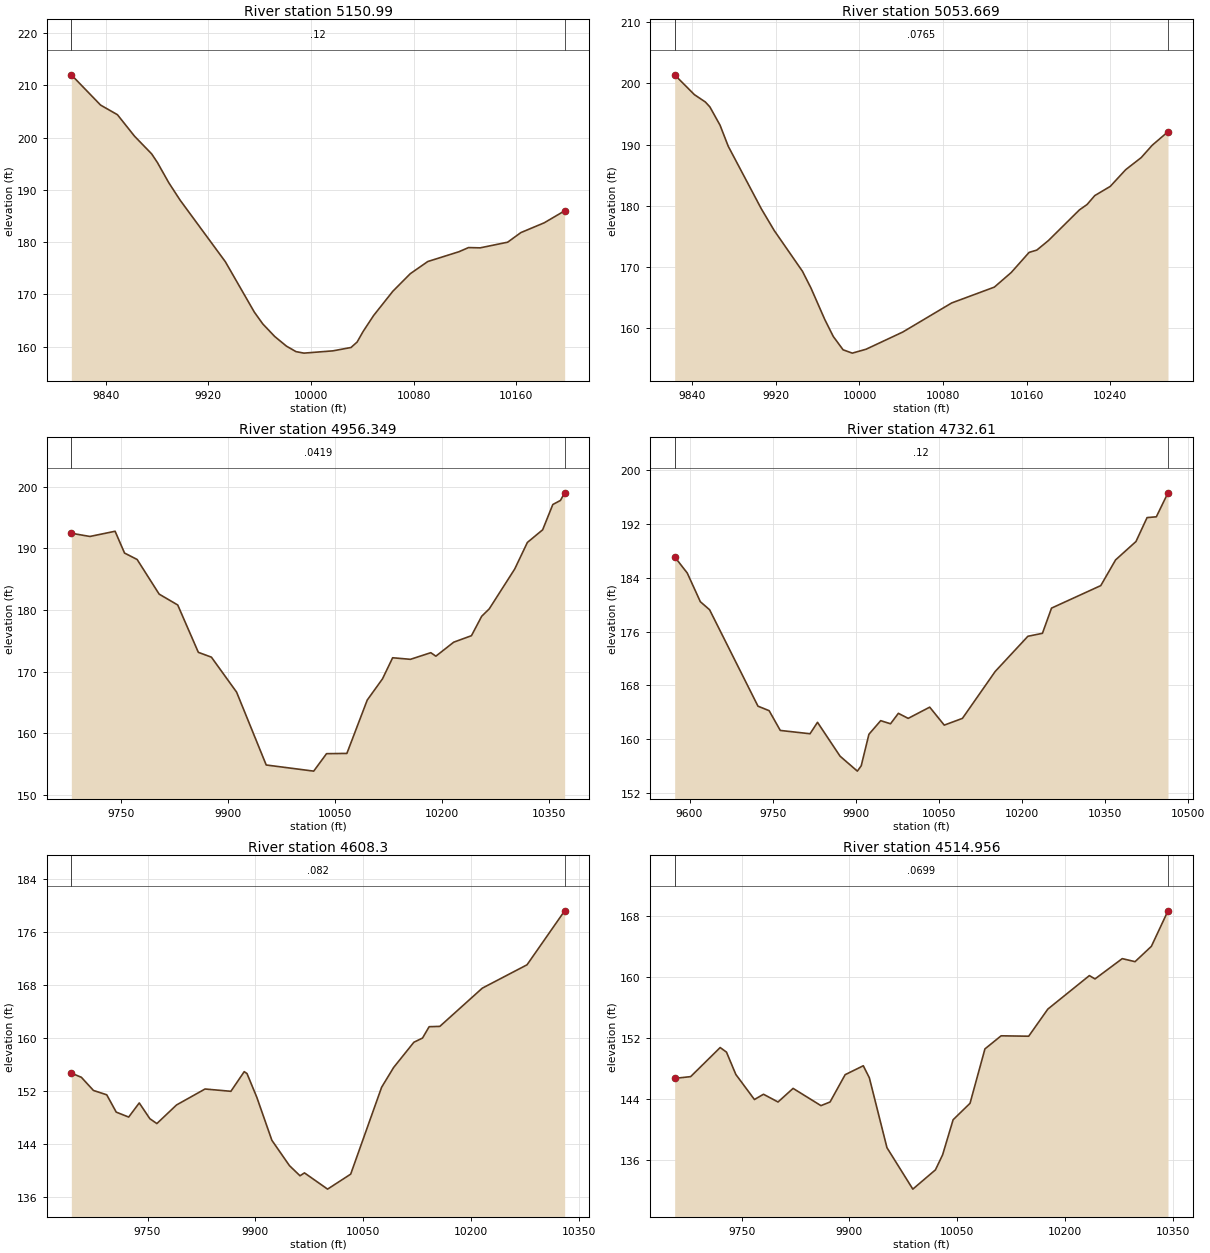
Type RM Length L Ch R = 1 , 5150.99,97.320400,97.320400,97.320400
XS GIS Cut Line= 6
1269129.22927886621914.3927284481269016.88667998621811.663640022
1268993.65084186621787.5642021151268992.34098071621786.052823991
1268958.52987695621750.5600053821268851.67485586621648.492892279
#Sta/Elev= 30
9813.293212.0035 9836.11206.21359849.228 204.3779862.565200.26269875.902196.8851
9880.348195.24569889.239191.3743 9898.13188.01939933.345176.25569955.925 166.623
9962.515164.36539971.818161.96249980.933160.12079988.405 159.0669994.605158.7808
 10017.2159.216510031.25159.856110036.01160.892910040.76162.944710048.92165.9838
10063.87170.612210077.49173.9761 10091.1176.298610115.36178.168410122.86178.9668
10131.93178.914810153.36179.994510163.69181.836310181.84183.700710197.79185.9982
#Mann= 3 , 0 , 0
9813.293    0.12       09813.293    0.12       010197.79    0.12       0
#XS Ineff= 2 , 0
       0                               0
Bank Sta=9813.293,10197.79
Exp/Cntr=0.3,0.1

Type RM Length L Ch R = 1 ,5053.669,97.320400,97.320400,97.320400
XS GIS Cut Line= 5
1269196.74672249  621839.38288791269065.51947454621722.212176815
1269064.03959432621720.8668312731268987.16561371621652.294059679
 1268817.4435412621563.955585182
#Sta/Elev= 30
9823.075201.39159841.942198.15239852.378196.95989856.777196.14929866.572193.1392
 9874.37189.7113 9905.98179.50789918.353175.94789945.388169.2842 9953.54166.5428
9966.735161.41299974.944158.61399984.328156.43799993.125155.896610006.33156.5345
 10041.5159.347710088.27164.0985 10129.1166.685310145.27169.076310162.39172.3635
10169.78172.741710180.88174.299410210.47179.299710217.86 180.19110225.26181.6493
10240.06183.152510254.85185.887810269.65187.852110280.28189.886310295.35192.0901
#Mann= 3 , 0 , 0
9823.075  0.0765       09823.075  0.0765       010295.35  0.0765       0
#XS Ineff= 2 , 0
       0                               0
Bank Sta=9823.075,10295.35
Exp/Cntr=0.3,0.1

Type RM Length L Ch R = 1 ,4956.349,223.739000,223.739000,223.739000
XS GIS Cut Line= 6
 1269368.1774416 621842.836197541269268.18169758621753.171947956
 1269193.8020798621690.6275959461269148.36572769621657.220160678
1269097.40189046621630.5129117521268779.01761529621496.189381495
#Sta/Elev= 30
9680.709192.44359706.772191.92289742.025192.76839755.245189.22849772.872 188.188
9803.718182.56549829.745 180.7999858.618 173.1159876.898172.33369912.198166.6566
9953.678154.831410020.18153.835410038.18156.669310066.67156.710310095.16165.3658
10116.52  168.8110130.77172.236110155.69 171.98210184.18173.0585 10191.3172.4929
10216.23  174.7610241.15175.818210255.43178.962210266.08 180.17410301.69 186.631
10319.49190.953610340.86193.0027 10355.1197.107210365.78197.7706 10371.7199.0052
#Mann= 3 , 0 , 0
9680.709  0.0419       09680.709  0.0419       0 10371.7  0.0419       0
#XS Ineff= 2 , 0
       09879.176                       0
Bank Sta=9680.709,10371.7
Exp/Cntr=0.3,0.1

Type RM Length L Ch R = 1 , 4732.61,124.309700,124.309700,124.309700
XS GIS Cut Line= 6
1269394.90303192621842.5435481521269341.51761529621595.147714823
1269307.50430509621486.7420435251269222.43486065621452.019821301
1268926.15303195621457.1268814951268793.34053198621431.085214823
#Sta/Elev= 30
9573.161187.11959595.962184.70219619.456180.45119636.238179.24159723.503164.9043
9743.641164.23199763.779 161.2929817.481160.80029830.957162.50439871.667157.4627
9902.859155.23879909.825 156.0289923.756160.72169945.006162.74649962.724162.2829
9976.898163.83839994.616163.087510033.47164.756310059.72162.082510092.53 163.088
10151.59170.059910210.66175.301510236.91 175.74110253.31179.491610342.17182.8395
10368.92 186.66410405.69189.395810425.75192.955410442.47193.077310463.52196.6431
#Mann= 3 , 0 , 0
9573.161    0.12       09573.161    0.12       010463.52    0.12       0
#XS Ineff= 2 , 0
       09967.602        10027.26       0
Bank Sta=9573.161,10463.52
Exp/Cntr=0.3,0.1

Type RM Length L Ch R = 1 ,  4608.3,93.344200,93.344200,93.344200
XS GIS Cut Line= 6
1269575.68337167621617.749428471  1269420.709249621478.283346092
1269335.89652118621387.7184458391269243.64800662621317.161318373
 1269130.2882534621237.1029618021269050.87887783621177.882585736
#Sta/Elev= 30
9643.979154.70989657.938154.07979674.761152.09149693.248 151.4389706.489148.8174
9723.806148.0732 9738.52150.20659753.234147.82749763.043147.09099790.351149.8971
9830.074 152.311 9866.05151.96259884.615154.93129888.494154.64299902.189151.0451
9923.072144.56959947.563140.73889962.258139.20569968.465139.640810000.64137.1894
10032.79139.451510075.86152.5791 10092.6155.566910120.72159.370510132.77160.0062
10142.01161.720610156.87161.769310215.94167.539610278.23171.069810330.61179.2209
#Mann= 3 , 0 , 0
9643.979   0.082       09643.979   0.082       010330.61   0.082       0
#XS Ineff= 2 , 0
       09890.396                       0
Bank Sta=9643.979,10330.61
Exp/Cntr=0.3,0.1

Type RM Length L Ch R = 1 ,4514.956,176.612100,176.612100,176.612100
XS GIS Cut Line= 6
1269668.82870449621569.1162638591269590.01912572621500.383008547
1269445.00899087621383.8571960521269361.69068589621308.088787949
1269210.99704888621214.1080378841269123.99128561 621154.26516231
#Sta/Elev= 30
9656.683146.67989678.908146.90819720.037150.72689728.823150.12169741.804147.1978
9767.702143.90579780.329144.59579800.551143.58059821.502145.36689860.297143.1022
9872.924143.57729893.968147.16499919.221148.33589927.639146.75659952.163137.5796
9988.155132.144710019.62134.674310029.59136.641810044.23141.251510067.76143.4083
10088.52150.549210111.03 152.26610149.42152.213210176.08 155.77410233.88 160.168
10241.71159.732910279.65 162.39610297.45161.997110320.18164.0111 10343.3168.6693
#Mann= 3 , 0 , 0
9656.683  0.0699       09656.683  0.0699       0 10343.3  0.0699       0
#XS Ineff= 2 , 0
       09922.204                       0
Bank Sta=9656.683,10343.3
Exp/Cntr=0.3,0.1

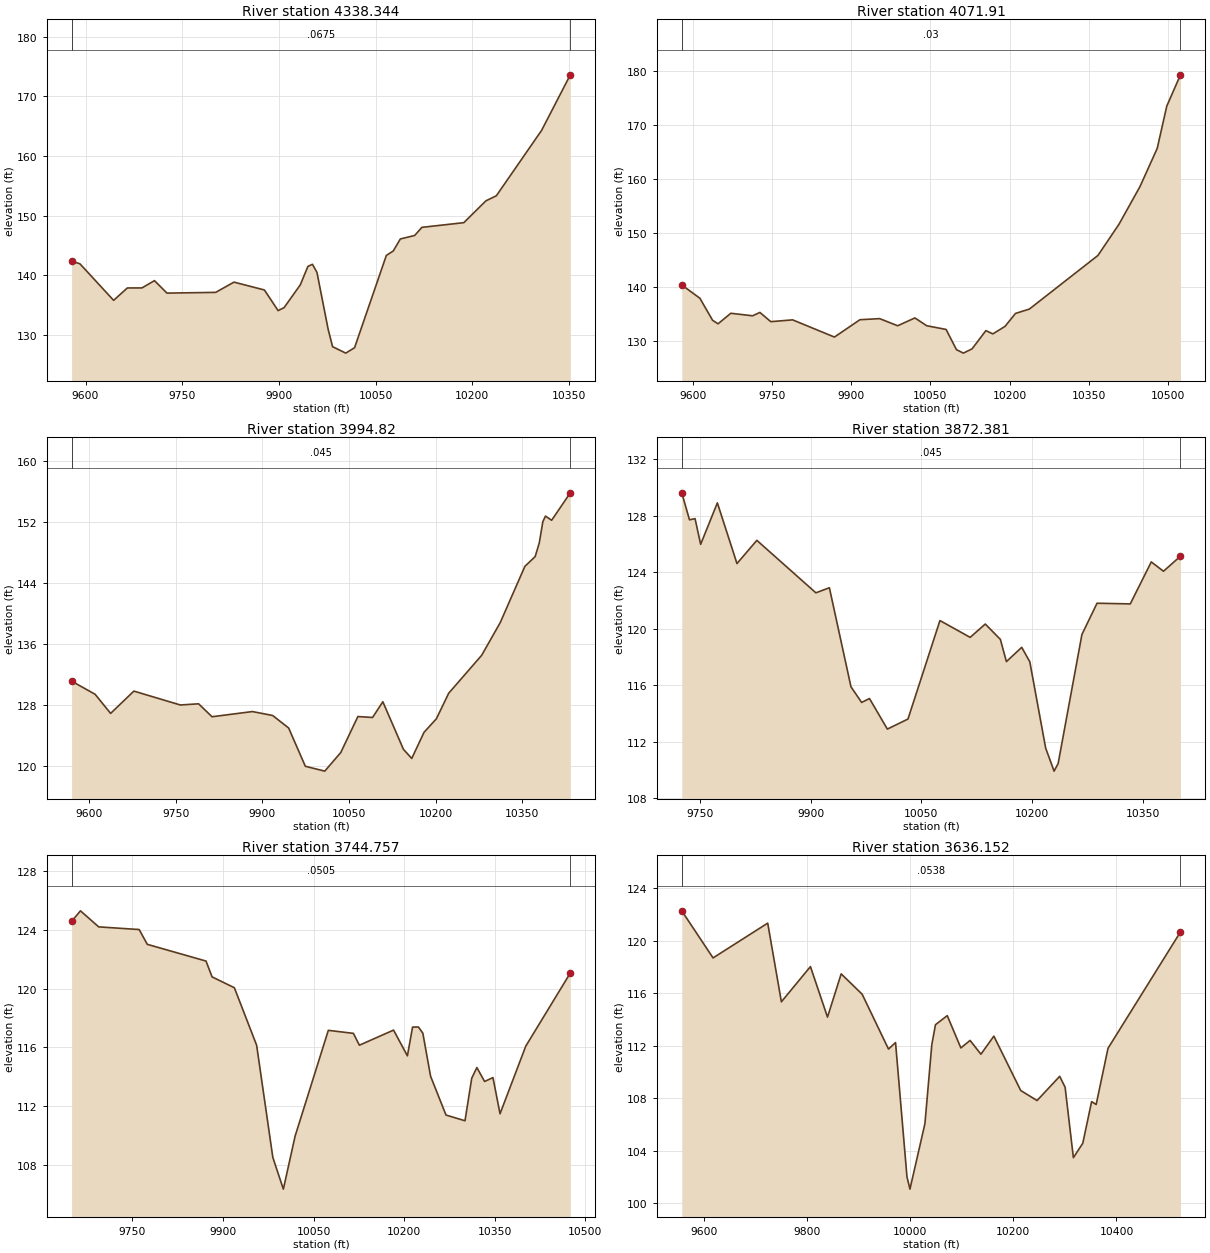
Type RM Length L Ch R = 1 ,4338.344,266.433700,266.433700,266.433700
XS GIS Cut Line= 6
 1269745.1779162621437.0024601971269625.98699754621290.380679682
1269572.41156483621251.6886499671269476.66113093621195.019186422
1269316.58350036621132.5352305321269127.56640953620993.759288147
#Sta/Elev= 30
9578.359142.40149591.355 141.9189643.577135.79779664.821137.87369687.537137.8818
9706.934139.10399726.332137.01219801.955137.13549830.283138.85419877.529 137.536
9898.805 134.0779908.088134.57949933.215138.39729945.002141.48819952.029141.8437
9959.053140.49819976.472130.92499983.308128.0275 10003.8 126.94810017.45127.8611
10066.71 143.32610077.46144.079110088.43146.091810110.66146.675210121.95148.0417
10186.93148.824910221.25152.487610237.42153.335410307.65164.303410352.18173.6155
#Mann= 3 , 0 , 0
9578.359  0.0675       09578.359  0.0675       010352.18  0.0675       0
#XS Ineff= 2 , 0
       09949.886                       0
Bank Sta=9578.359,10352.18
Exp/Cntr=0.3,0.1

Type RM Length L Ch R = 1 , 4071.91,77.090600,77.090600,77.090600
XS GIS Cut Line= 6
1269767.74736068621423.1135713161269653.14955974621061.293548167
 1269623.3764787621028.8774481121269552.88914308621001.397714809
1269317.21205971621017.0227148091269128.40997639620928.481048167
#Sta/Elev= 30
 9578.73140.37689613.038 137.9249637.171133.82689647.514133.17169671.658135.1281
9713.019 134.662 9726.81 135.2849747.496133.57099788.867133.90489868.163130.7136
 9916.43 133.9329953.807134.13359988.013132.813910020.67134.262910043.09132.8134
10079.77132.126710099.46128.373710112.58127.733610128.98128.526110155.23131.9079
10168.41131.304110191.49132.696610211.27135.097910237.65135.909510367.63145.8614
10407.49151.649110447.35158.651310479.96165.724910498.08173.565810524.05179.3732
#Mann= 3 , 0 , 0
 9578.73    0.03       0 9578.73    0.03       010524.05    0.03       0
#XS Ineff= 2 , 0
       0 9948.95        10076.78       0
Bank Sta=9578.73,10524.05
Exp/Cntr=0.3,0.1

Type RM Length L Ch R = 1 , 3994.82,122.438800,122.438800,122.438800
XS GIS Cut Line= 6
1269845.87236068 621315.474682421269802.46958286621110.613571301
1269759.14544129621041.3779190631269733.95049343621017.390317768
1269578.93080974620919.3664648231269253.40997639620781.345631495
#Sta/Elev= 30
 9569.62131.11099610.342129.38559637.172 126.8729677.415129.80219757.903127.9792
9789.481128.13449812.703126.43229882.578127.11419917.656126.59819945.334124.9569
9974.254119.921810007.86119.285510035.58121.729310065.21126.461610090.61126.3336
10108.42128.403910144.06122.155510158.45120.9473 10179.7124.385810201.08126.1652
10222.46129.527710279.48134.507910311.55138.792610354.31146.202210372.13147.4826
10379.26149.294410385.37152.060710389.95152.803610400.64152.256810432.95155.8639
#Mann= 3 , 0 , 0
 9569.62   0.045       0 9569.62   0.045       010432.95   0.045       0
#XS Ineff= 2 , 0
       09897.223         10063.5       0
Bank Sta=9569.62,10432.95
Exp/Cntr=0.3,0.1

Type RM Length L Ch R = 1 ,3872.381,127.623800,127.623800,127.623800
XS GIS Cut Line= 6
1269878.85847175621137.0892657341269793.84080639620994.314230323
 1269762.2053214620930.0878828761269740.25675833620868.569113463
1269720.00430512 620827.193432421269458.28555509 620631.88093242
#Sta/Elev= 30
9725.531129.62799735.999127.71639743.555 127.7989751.112125.97629773.781128.9156
 9800.35124.61479827.284126.25989907.274122.5406 9925.56122.90089954.818115.8796
9969.262 114.7719979.902115.047410004.14112.881410032.07113.594810075.38120.5738
10116.32119.383710136.82120.327510157.25119.240210165.44117.664210186.19118.6768
10197.16 117.65210218.66111.530510230.08109.902110235.56110.442410267.78119.5876
10288.25 121.80210333.28121.754710361.73124.729510378.31124.069710401.32125.1395
#Mann= 3 , 0 , 0
9725.531   0.045       09725.531   0.045       010401.32   0.045       0
#XS Ineff= 2 , 0
       09890.482        10072.34       0
Bank Sta=9725.531,10401.32
Exp/Cntr=0.3,0.1

Type RM Length L Ch R = 1 ,3744.757,108.605200,108.605200,108.605200
XS GIS Cut Line= 6
1269949.17097178621217.8184324061269878.78820711620883.918357566
1269874.87896332620875.386224613 1269872.3371754620869.395008713
1269844.81406185620832.0601069481269575.47305512 620506.88093242
#Sta/Elev= 30
9649.201124.57289663.876125.29149694.053124.20079761.111124.01869774.523123.0131
9871.758121.87619881.817120.80029918.699120.06259955.581116.15299982.405 108.524
9999.835106.370310019.29109.975410074.29117.165110115.76 116.96210125.73116.1552
 10182.3117.181710205.23115.432410213.75117.385510223.45117.392810230.79116.9697
10243.57114.049110269.13111.4069 10300.6111.017710311.73113.911410320.25114.6342
10333.03113.688910346.89113.953710358.59 111.49310401.19116.090210474.96121.0644
#Mann= 3 , 0 , 0
9649.201  0.0505       09649.201  0.0505       010474.96  0.0505       0
#XS Ineff= 2 , 0
       0 9919.65         10098.9       0
Bank Sta=9649.201,10474.96
Exp/Cntr=0.3,0.1

Type RM Length L Ch R = 1 ,3636.152,179.328800,179.328800,179.328800
XS GIS Cut Line= 6
1270033.80638844621243.8600990621269989.53555515620931.360099077
1269959.28456065 620823.201241271269927.03555509620743.860099077
1269802.03555509620586.3080157341269614.53555509620417.037182406
#Sta/Elev= 30
9556.866122.27479617.552118.68949723.587121.33819750.096115.34659806.427118.0283
9839.563 114.1829866.072117.47589906.772115.92359957.874111.74719971.501112.2449
9993.688102.02299999.462101.084510028.51106.071310041.88112.088510048.94113.6022
10071.79114.294810098.19111.836510116.15112.405910137.09111.357110162.22112.7326
10214.31 108.59310245.98107.829810289.93109.674210300.41108.840510316.45103.4795
10334.68104.576310351.81 107.74810360.65107.527310383.64111.809710524.17120.6675
#Mann= 3 , 0 , 0
9556.866  0.0538       09556.866  0.0538       010524.17  0.0538       0
#XS Ineff= 2 , 0
       09889.001        10059.19       0
Bank Sta=9556.866,10524.17
Exp/Cntr=0.3,0.1

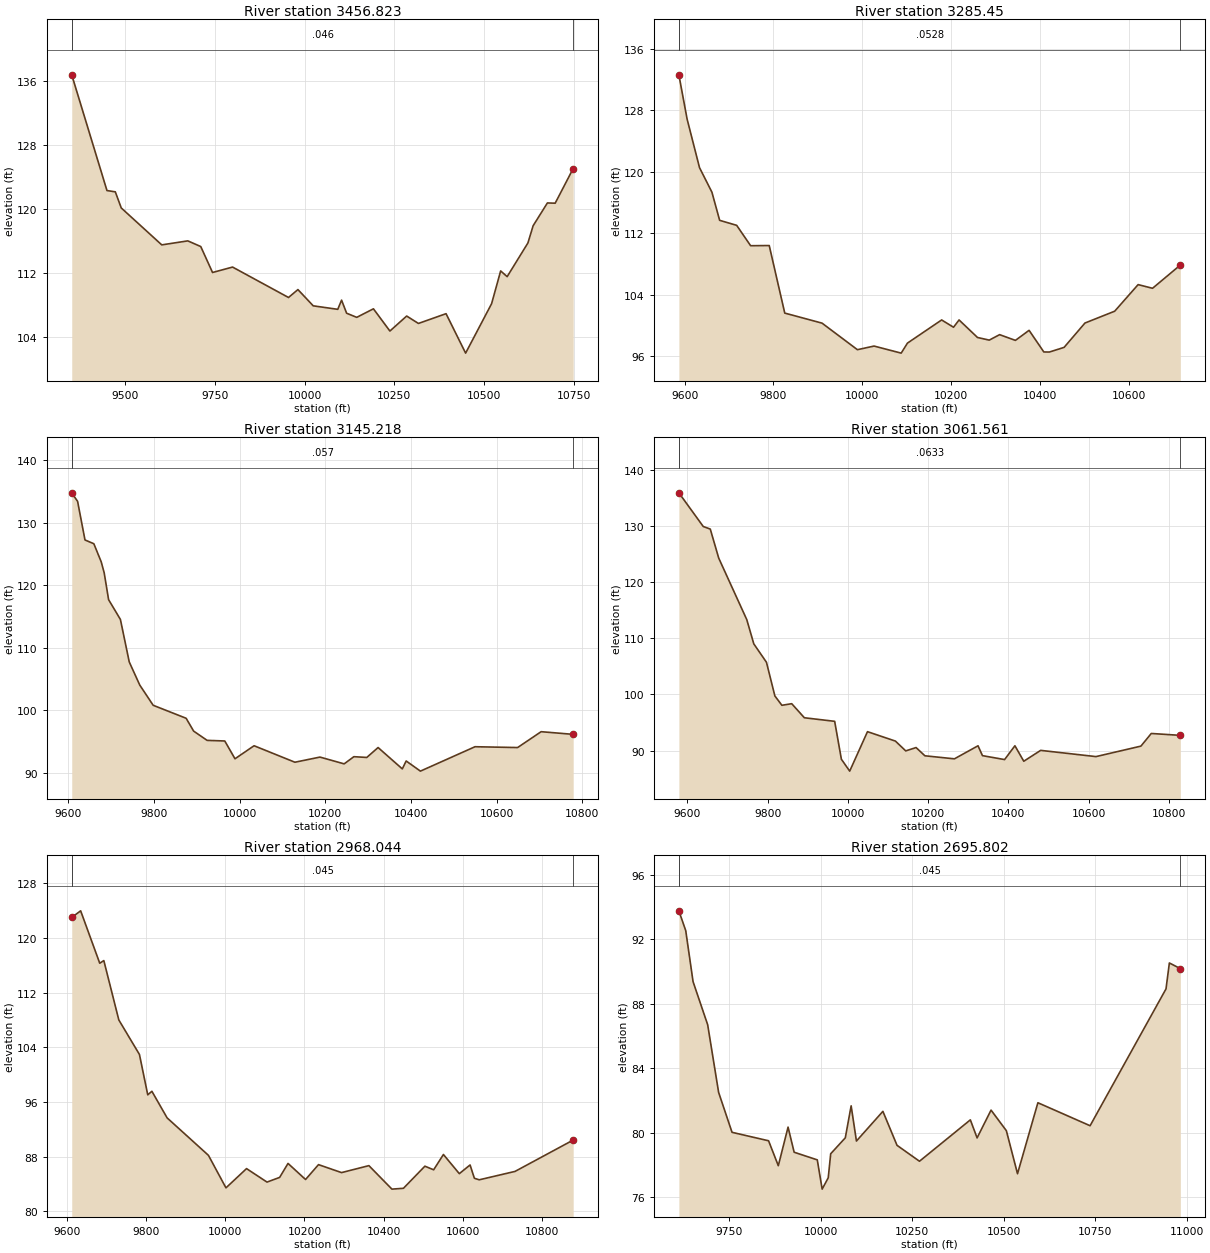
Type RM Length L Ch R = 1 ,3456.823,171.372400,171.372400,171.372400
XS GIS Cut Line= 6
 1270159.2259486621434.9914648091270115.38914305621155.043548167
1270127.48924828620735.1707207411270086.74330971620632.908131495
1269910.96205974620484.4706314951269591.95164305 620336.03313148
#Sta/Elev= 30
9350.693136.79099448.894122.33629472.139122.17759488.744120.16449601.651115.5524
9674.252116.0525 9710.37115.34399743.204112.1045 9799.05112.78099954.962108.9817
9981.224109.969310023.91107.939610092.29107.503610102.88108.651510116.97107.0165
10145.16106.501710191.69107.567410237.62104.791310284.37106.664710317.13105.7395
10394.11106.960210448.67102.033310521.04108.203910546.37112.298910564.47111.5857
10622.36115.793610636.84117.940610676.64120.790310698.35120.758810748.58125.0917
#Mann= 3 , 0 , 0
9350.693   0.046       09350.693   0.046       010748.58   0.046       0
#XS Ineff= 2 , 0
       09903.712        10100.49       0
Bank Sta=9350.693,10748.58
Exp/Cntr=0.3,0.1

Type RM Length L Ch R = 1 , 3285.45,140.232200,140.232200,140.232200
XS GIS Cut Line= 6
1270428.77166623621125.8045435251270301.50873014 620776.56804122
1270279.98679405620699.2887641791270271.61525768620675.030274615
1270017.33201435 620346.614696221269826.35979211620207.725807309
#Sta/Elev= 30
9587.007132.60829605.594126.83129633.487  120.529661.381117.32849678.814113.6592
9717.167113.00799748.547110.35219790.447110.37639825.417101.57939909.346100.2705
9988.99396.8126210026.4697.2840310087.5596.3649610101.6797.6691610178.65100.6865
 10205.499.7354710217.85100.686810259.3498.4041710285.8398.0584910309.1398.77082
10344.7898.0241110375.5299.3333410408.7296.5172810421.1796.5064910454.36 97.1144
10501.33100.285810568.27101.823810621.03105.287410653.48104.808810716.08 107.836
#Mann= 3 , 0 , 0
9587.007  0.0528       09587.007  0.0528       010716.08  0.0528       0
#XS Ineff= 2 , 0
       09897.107        10109.43       0
Bank Sta=9587.007,10716.08
Exp/Cntr=0.3,0.1

Type RM Length L Ch R = 1 ,3145.218,83.656900,83.656900,83.656900
XS GIS Cut Line= 6
1270539.85160685621049.1690177321270496.96794069620915.662471414
1270431.71706346620738.8076245491270401.82359102620637.269857943
 1270182.2625699620249.392473966 1269963.5125699620058.420251742
#Sta/Elev= 30
9607.968134.81999621.656133.45019638.886127.26989659.562126.66579676.791123.7658
9683.683122.02249694.021117.70919721.588114.54159742.264107.7262 9766.87104.0145
9798.128100.78929875.06398.707539892.54896.652819924.02195.168629965.24695.07097
9989.10892.2220310033.6594.3079210128.9791.6679810187.4592.49148   1024491.40696
10266.6292.5546210296.7892.4352110323.1794.0210410379.7290.6002110388.7191.86906
10422.0190.2428110549.4894.1508510648.9394.01934 10703.896.5594510778.6896.13263
#Mann= 3 , 0 , 0
9607.968   0.057       09607.968   0.057       010778.68   0.057       0
#XS Ineff= 2 , 0
       09883.753        10034.63       0
Bank Sta=9607.968,10778.68
Exp/Cntr=0.3,0.1

Type RM Length L Ch R = 1 ,3061.561,93.517100,93.517100,93.517100
XS GIS Cut Line= 6
1270634.42774919621057.0040413291270515.01554054620736.512645572
 1270506.6259611620708.8118940591270497.13514742620661.715823621
1270281.22090325  620235.50358511270012.12368101620006.336918429
#Sta/Elev= 30
9578.561135.92829639.343129.92689656.849 129.4679677.856124.30459747.879113.3258
9765.385109.00799796.896105.73329817.90399.728949835.40898.062869859.91798.34818
9891.42795.842029966.97495.207229983.73988.4504210004.4686.3308810048.8193.36292
10118.42 91.684310144.1789.9378310169.9290.5309510191.9989.0634910265.56 88.5221
10324.4190.8470810335.45 89.090510390.6288.3900910416.3790.8514610438.4488.09214
10480.5790.0291710618.4788.9200710730.5190.7872110756.36 93.0411 10828.892.70505
#Mann= 3 , 0 , 0
9578.561  0.0633       09578.561  0.0633       0 10828.8  0.0633       0
#XS Ineff= 2 , 0
       09949.716        10044.69       0
Bank Sta=9578.561,10828.8
Exp/Cntr=0.3,0.1

Type RM Length L Ch R = 1 ,2968.044,272.242800,272.242800,272.242800
XS GIS Cut Line= 6
1270700.00785682620978.8565177321270657.12419066620845.349971399
1270591.87331343620668.4951245491270561.97984102620566.957357943
1270387.12368101620202.5174739811270045.10979208619943.836918429
#Sta/Elev= 30
9611.684 122.9879634.225123.95669682.468116.28829692.805116.67489730.711107.9879
9782.852102.93439803.83497.030519814.32597.546969852.79293.656379957.26688.17328
10001.5783.4140410053.5686.2322810105.3584.2570310137.2584.9464810158.4586.98977
10202.75 84.6386 10235.586.8128510293.7385.6474810362.8786.6672610421.09 83.2291
 10450.283.3516910504.4386.5854710526.5886.0578210551.26 88.296810591.4585.49249
10618.64 86.767310629.5284.8178110641.7684.5927410732.2685.8209910879.3490.41079
#Mann= 3 , 0 , 0
9611.684   0.045       09611.684   0.045       010879.34   0.045       0
#XS Ineff= 2 , 0
       09954.892         10037.3       0
Bank Sta=9611.684,10879.34
Exp/Cntr=0.3,0.1

Type RM Length L Ch R = 1 ,2695.802,0.000000,0.000000,0.000000
XS GIS Cut Line= 4
1270833.30423656620841.4063628611270756.91534767620383.073029518
 1270526.0125699620134.8091406381270038.16534767619848.350807309
#Sta/Elev= 30
9612.59193.747549631.37192.516899651.32889.356289691.241 86.68279721.17682.48482
9757.763 80.01189857.545 79.48769884.15477.941499910.76380.333919927.393 78.7764
9990.58978.3031810003.8976.4890210020.5277.1933810027.1878.6815810067.0979.66991
10083.0481.6539710097.4979.4711410169.7581.3129810208.2979.2058810269.6778.21819
10408.5680.7841710427.0379.6654910465.0881.3895810506.9380.1115210537.3777.44335
10593.0281.8458810735.5680.42081 10942.988.9077410952.07 90.514110982.0290.16348
#Mann= 3 , 0 , 0
9612.591   0.045       09612.591   0.045       010982.02   0.045       0
#XS Ineff= 2 , 0
       09911.358        10057.42       0
Bank Sta=9612.591,10982.02
Exp/Cntr=0.3,0.1